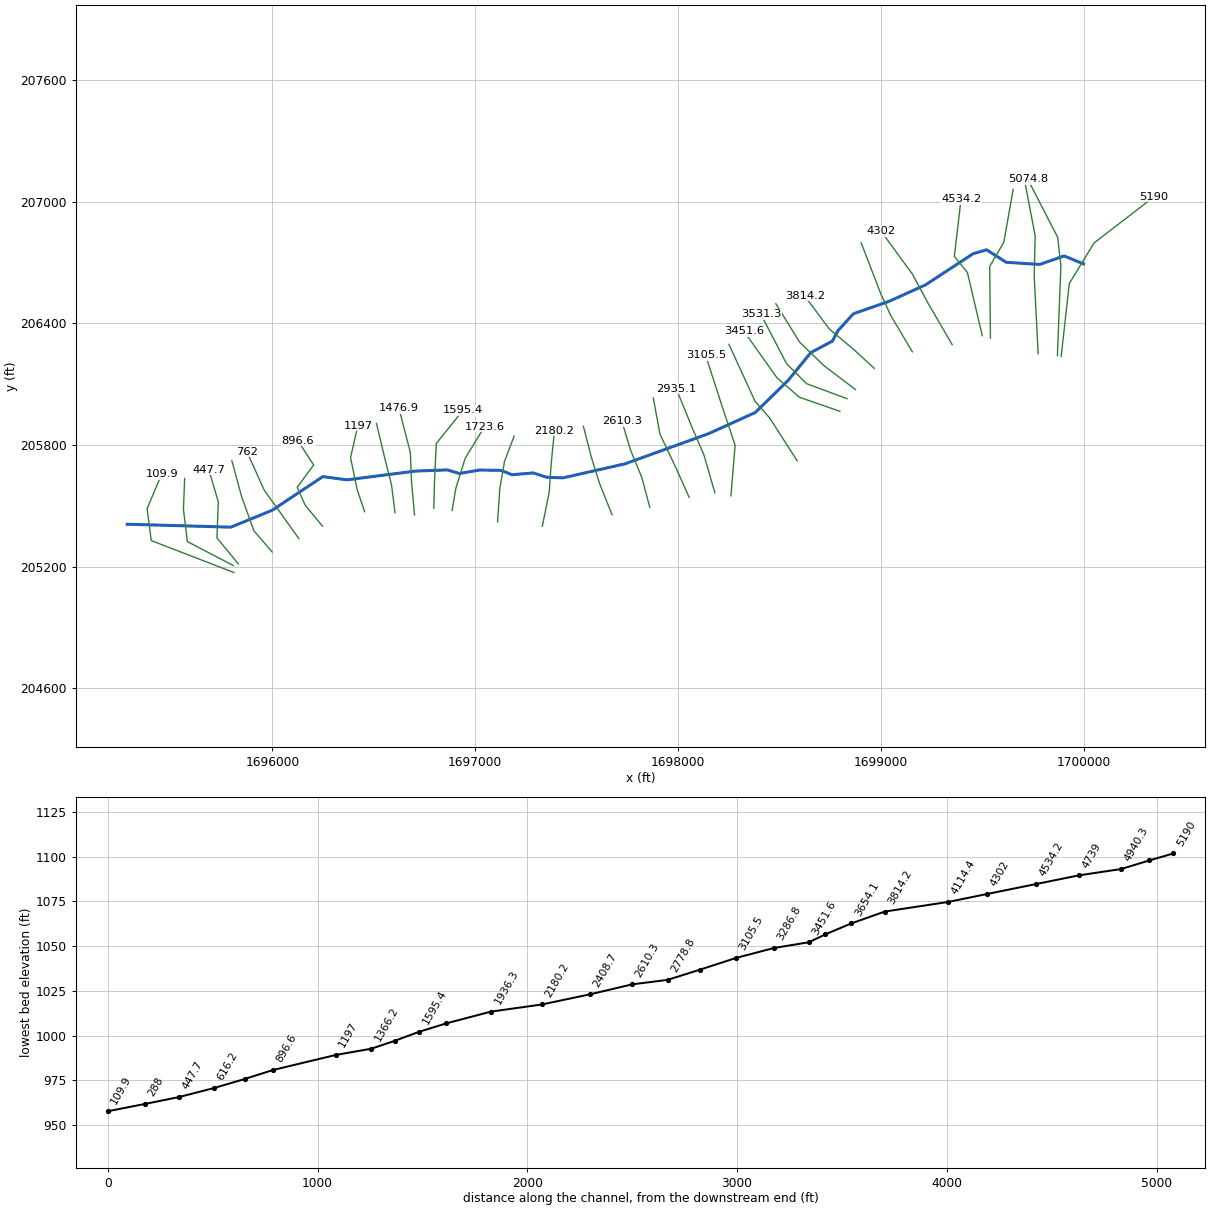
--- lftfrksprn.prj (project) ---

Proj Title=lftfrksprn
Current Plan=p01
Default Exp/Contr=0,0
English Units
Geom File=g01
Flow File=f01
Plan File=p01
BEGIN DESCRIPTION:
END DESCRIPTION:
DSS Export Rating Curves= 0
DSS Export Rating Curve Sorted= 0
DSS Export Volume Flow Curves= 0
DXF OffsetX= 0
DXF OffsetY= 0
DXF ScaleX= 0
DXF ScaleY= 0

--- lftfrksprn.p01 (plan) ---

Plan Title=Floodplain
Program Version=4.00
Geom File=g01
Flow File=f01
K Sum by GR=0
Std Step Tol=0.01
Critical Tol=0.01
Num of Std Step Trials=20
Max Error Tol=0.3
Flow Tol Ratio=0.001
Split Flow NTrial=30
Split Flow Tol=0.02
Split Flow Ratio=0.02
Log Output Level=0
Friction Slope Method=1
Unsteady Friction Slope Method=2
Unsteady Bridges Friction Slope Method=1
Global Log Level=0
CheckData=False
Run HTab=0
Run UNet=0
Run PostProcess=0
UNET Theta=0
UNET Theta Warmup=0
UNET ZTol=0
UNET ZSATol=0
UNET MxIter=0
UNET MaxInSteps=0
UNET DtIC=0
UNET DtMin=0
UNET MaxCRTS=0
UNET WFStab=0
UNET SFStab=0
UNET WFX=0
UNET SFX=0
UNET DSS MLevel=0
UNET DZMax Abort=0
UNET Convert EG Bridges=0
UNET Use Existing IB Tables=0
UNET Froude Limit=0
UNET Froude Power=0
Write IC File=0
Echo Input=False
Echo Output=False
Write Detailed=0

--- lftfrksprn.f01 (steady flow) ---

Flow Title=NFF Regression Equation
Program Version=4.00
Number of Profiles= 1
Profile Names=P100yr
River Rch & RM=lftfrksprn,Main            ,5190
     384
River Rch & RM=lftfrksprn,Main            ,3531.3
     417
River Rch & RM=lftfrksprn,Main            ,1476.9
     460
River Rch & RM=lftfrksprn,Main            ,288
     510
Boundary for River Rch & Prof#=lftfrksprn,Main            , 1
Up Type= 0
Dn Type= 3
Dn Slope=0.02
DSS Import GetInterval= 0
DSS Import GetPeak= 0
DSS Import FillOption= 0

--- lftfrksprn.g01 (geometry) ---

Geom Title=USGS 10m DEM
Program Version=4.00

River Reach=lftfrksprn      ,Main
Reach XY= 30
     1699999.987      206692.481     1699904.406       206731.59
     1699784.254      206689.877     1699619.334      206700.257
     1699521.746      206762.095     1699455.464      206742.553
     1699221.456      206589.295     1699040.792      206507.658
      1698865.68      206446.783     1698789.034      206363.127
     1698761.793      206311.879     1698655.481      206255.138
     1698544.388      206119.024     1698381.549      205959.686
     1698150.203       205854.88     1697739.051      205706.531
     1697433.109      205637.316     1697353.481      205640.194
     1697285.366       205661.78     1697182.234      205652.666
     1697128.029      205674.252     1697022.432      205676.072
     1696922.556      205658.916     1696862.331      205676.679
     1696706.087      205670.873      1696367.91      205627.597
      1696249.11      205643.512     1695999.005      205477.442
     1695795.598      205394.306     1695284.045      205408.825

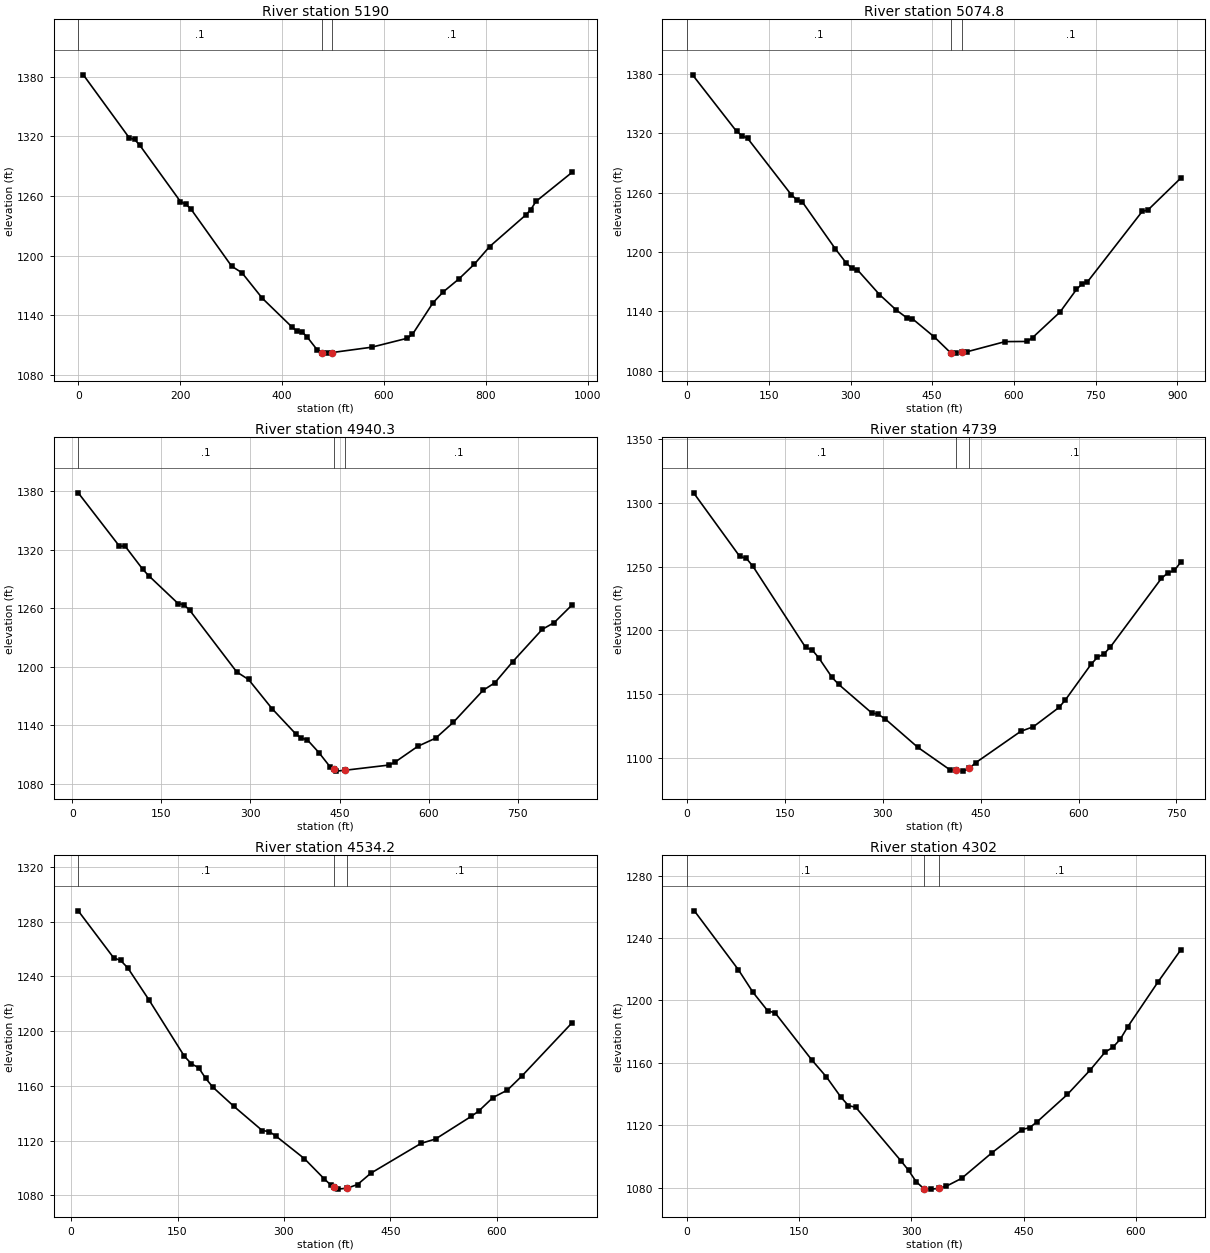
Type RM Length L Ch R = 1 ,5190    ,98.6,115.3,132
XS GIS Cut Line= 4
     1699890.012      206236.299     1699929.909      206595.619
     1700051.793      206795.509      1700347.97      207023.432
#Sta/Elev= 30
      10 1382.13   100.4 1318.48   110.5 1317.05   120.5 1311.46   200.8 1254.39
   210.9 1251.84   220.9  1247.2   301.3 1189.28   321.4 1182.78   361.5 1157.02
   420.1 1127.86   429.8 1123.78   439.6 1123.12   449.3 1118.15   468.8 1105.32
   478.3 1102.07   488.3 1101.76   498.3 1102.33   576.1 1107.72   646.2 1116.76
   656.3 1120.68   696.7 1152.54   716.9 1163.54   747.2 1176.38   777.5 1191.25
   807.8  1209.1   878.5  1240.8   888.6 1246.35   898.7 1254.56   969.4 1283.78
#Mann= 3 , 0 , 0
       0      .1       0   478.3    .045       0   498.3      .1       0
Bank Sta=478.3,498.3
XS Rating Curve= 0 ,0
Exp/Cntr=0.3,0.1

Type RM Length L Ch R = 1 ,5074.8  ,138,134.4,130.9
XS GIS Cut Line= 4
     1699871.405      206240.938     1699888.468      206684.594
     1699872.623      206823.542     1699725.144      207109.969
#Sta/Elev= 30
    10.1 1379.23    90.8 1322.14   100.9 1317.69     111 1315.14   191.7 1257.73
   201.8 1252.76   211.9 1250.47   272.4 1203.08   292.6 1188.62   302.7  1183.6
   312.8 1181.99   353.2 1157.04   383.4 1141.66   403.6 1133.42   413.7 1132.53
     454 1114.06   483.9 1098.06   493.9 1097.82   503.9 1099.26   513.9 1099.22
   583.8 1109.46   624.1 1109.62   634.2 1113.54   684.5 1139.36   714.7 1162.24
   724.8 1167.73   734.8 1169.86   835.5 1241.25   845.6 1242.42     906 1274.73
#Mann= 3 , 0 , 0
       0      .1       0   483.9    .045       0   503.9      .1       0
Bank Sta=483.9,503.9
XS Rating Curve= 0 ,0
Exp/Cntr=0.3,0.1

Type RM Length L Ch R = 1 ,4940.3  ,214.2,201.3,188.4
XS GIS Cut Line= 4
     1699776.335      206249.469     1699756.834      206634.622
     1699761.709      206830.855     1699712.956      207085.592
#Sta/Elev= 30
     9.9 1378.43    79.1 1323.84      89 1323.64   118.7 1299.91   128.5 1293.51
     178 1264.93   187.9 1263.65   197.8 1257.89   276.9 1194.69   296.7    1187
   336.2 1157.17   375.8 1131.46   385.6 1126.78   395.5 1125.25   415.1 1112.12
   434.7  1096.9  440.25  1094.8   444.5 1093.03  459.81 1093.96   532.9 1099.24
   542.7 1101.99   581.9 1118.54   611.9 1126.88   641.8 1143.24   691.7  1175.9
   711.6 1183.68   741.5  1205.2   791.4 1238.47   811.4 1245.32   841.3 1263.33
#Mann= 3 , 0 , 0
     9.9      .1       0  440.25    .045       0  459.81      .1       0
Bank Sta=440.25,459.81
XS Rating Curve= 0 ,0
Exp/Cntr=0.3,0.1

Type RM Length L Ch R = 1 ,4739    ,173.9,204.8,235.7
XS GIS Cut Line= 4
     1699541.099      206326.256     1699537.443      206679.719
     1699606.917      206799.165     1699653.233      207059.997
#Sta/Elev= 30
    10.1 1308.04    80.8 1258.09    90.9 1256.61     101 1250.33   181.8 1186.58
   191.9  1184.6     202 1178.39   222.2 1163.12   232.3 1157.65   282.8  1135.3
   292.9 1134.07     303  1130.8   353.5 1108.25   402.8 1090.57   412.6    1090
   422.6 1089.49   432.6 1091.66   442.3 1096.06   511.3  1120.7   530.9 1124.39
   570.2 1139.56     580 1145.54   619.2 1173.39     629 1178.94   638.8 1181.46
   648.6 1186.85   727.1 1240.94     737 1245.21   746.8 1247.05   756.6 1253.57
#Mann= 3 , 0 , 0
       0      .1       0   412.6    .045       0   432.6      .1       0
Bank Sta=412.6,432.6
XS Rating Curve= 0 ,0
Exp/Cntr=0.3,0.1

Type RM Length L Ch R = 1 ,4534.2  ,236.8,232.3,227.7
XS GIS Cut Line= 4
     1699500.878      206338.444     1699427.748      206649.248
     1699363.149      206729.692     1699396.058      207011.243
#Sta/Elev= 30
      10 1287.81    59.9 1253.52    69.8 1251.55    79.8 1246.18   109.8 1222.71
   159.6 1181.66   169.6 1176.07   179.6 1173.33   189.6 1165.55   199.6 1159.14
   229.5 1145.02   269.4  1127.4   279.4 1126.64   289.4 1123.05   328.7 1106.91
   356.8 1092.09   366.2 1087.52  370.23 1086.26   375.6 1084.62  388.86  1085.3
   403.7 1087.98   422.5 1096.27   493.3 1118.05   513.6  1121.2   564.2 1137.83
   574.3 1141.53   594.6  1151.5   614.8 1156.86   635.1 1167.07   705.9 1205.97
#Mann= 3 , 0 , 0
      10      .1       0  370.23    .045       0  388.86      .1       0
Bank Sta=370.23,388.86
XS Rating Curve= 0 ,0
Exp/Cntr=0.3,0.1

Type RM Length L Ch R = 1 ,4302    ,189.1,187.5,186
XS GIS Cut Line= 4
      1699352.18      206294.566     1699233.952      206498.112
     1699157.165      206640.716     1699002.373      206852.794
#Sta/Elev= 30
     9.8  1257.4    68.7 1219.62    88.3 1205.11   107.9  1193.3   117.7 1192.05
   166.7 1161.89   186.4 1150.93     206 1137.84   215.8 1132.59   225.6 1131.51
     286 1097.16   296.1 1091.14   306.2  1083.9   316.5 1079.38   326.5 1079.09
   336.5 1079.53   346.7    1081     367 1085.98   407.5 1102.37   447.8 1117.28
   457.9 1118.47     468 1122.25   508.4 1139.75   538.7 1155.31   558.9 1166.92
     569 1169.87   579.1 1175.14   589.2  1183.2   629.6 1211.87   659.9 1232.34
#Mann= 3 , 0 , 0
       0      .1       0   316.5    .045       0   336.5      .1       0
Bank Sta=316.5,336.5
XS Rating Curve= 0 ,0
Exp/Cntr=0.3,0.1

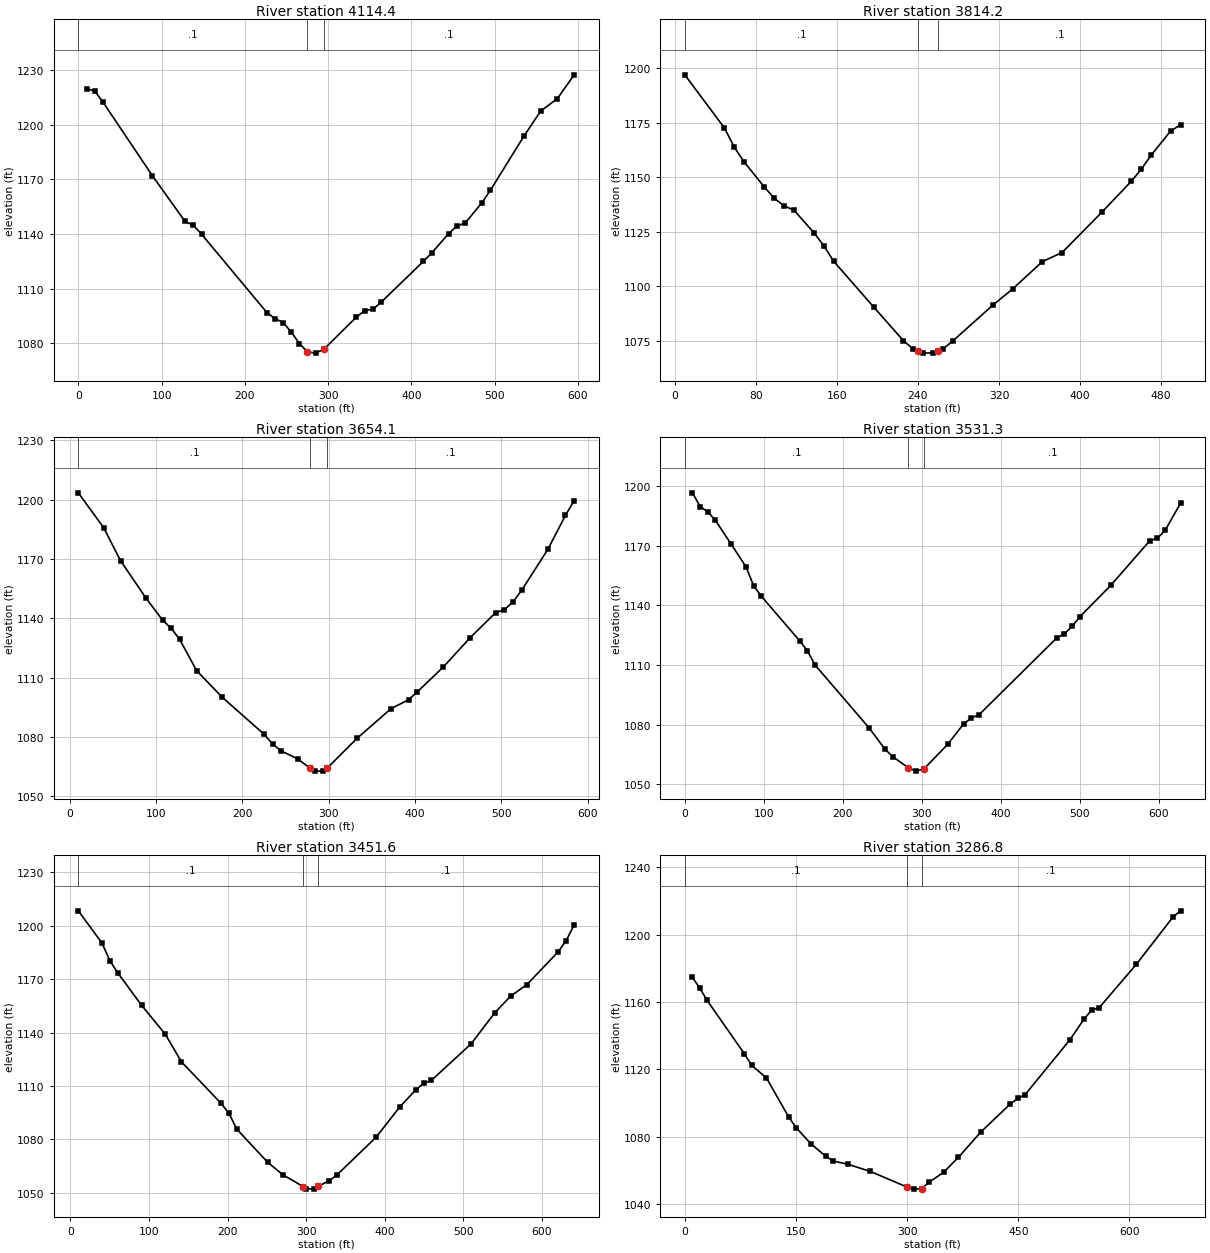
Type RM Length L Ch R = 1 ,4114.4  ,289.2,300.3,311.3
XS GIS Cut Line= 4
     1699155.947       206259.22     1699049.908       206437.17
     1699001.154      206543.209     1698903.647      206796.728
#Sta/Elev= 30
     9.9 1219.84    19.7 1218.47    29.6 1212.41    88.8 1172.09   128.2 1146.89
   138.1 1144.84     148  1139.9   226.6 1096.79   236.3 1093.53   246.1 1091.38
   255.8  1086.1   265.5 1079.89     275 1075.36     285 1074.61     295 1076.77
   333.9 1094.37     344 1097.97     354 1098.73   364.1 1102.75   414.4 1124.96
   424.5 1129.62   444.6 1140.15   454.6 1144.38   464.7 1146.07   484.8  1157.2
   494.9 1164.02   535.1 1193.68   555.2 1207.42   575.4 1214.37   595.5 1227.38
#Mann= 3 , 0 , 0
       0      .1       0     275    .045       0     295      .1       0
Bank Sta=275,295
XS Rating Curve= 0 ,0
Exp/Cntr=0.3,0.1

Type RM Length L Ch R = 1 ,3814.2  ,161.6,160,158.2
XS GIS Cut Line= 4
     1698968.245      206177.558     1698867.082       206270.19
     1698746.417      206371.353     1698624.533      206535.896
#Sta/Elev= 30
     9.8 1196.89      49 1172.47    58.8 1163.59    68.6 1156.84    88.2 1145.52
      98 1140.34   107.8 1136.84   117.6 1134.83   137.2 1124.55     147 1118.57
   156.8  1111.4   196.2 1090.48   225.7 1074.98   235.6 1071.06  239.96 1070.25
   245.4 1069.28   255.3 1069.43  260.07 1070.31   265.1 1071.32   274.9 1075.04
   314.1 1091.33   333.6 1098.75   362.9 1111.26   382.4 1115.42   421.4  1133.8
   450.6 1148.02   460.4 1153.51   470.1 1159.93   489.6 1171.18   499.4 1173.95
#Mann= 3 , 0 , 0
     9.8      .1       0  239.96    .045       0  260.07      .1       0
Bank Sta=239.96,260.07
XS Rating Curve= 0 ,0
Exp/Cntr=0.3,0.1

Type RM Length L Ch R = 1 ,3654.1  ,123.5,122.8,122.4
XS GIS Cut Line= 4
     1698875.614      206072.738     1698719.603      206190.965
     1698600.156      206306.755     1698483.148      206495.675
#Sta/Elev= 30
     9.8 1203.46    39.1 1185.85    58.7 1169.13    88.1 1150.25   107.7 1138.87
   117.4 1134.91   127.2  1129.3   146.8 1113.53   176.2 1100.15   225.1 1081.27
   234.9 1076.35   244.7 1072.89   264.2 1068.78  278.43 1064.05   283.8  1062.7
   293.6 1062.64  297.95 1064.09   332.7 1079.22   372.2 1094.28   392.4 1098.74
   402.5 1102.74   432.8 1115.37   463.1 1129.83   493.4  1142.9   503.5 1144.31
   513.6 1148.38   523.7 1154.27     554 1174.98   574.2 1192.04   584.3 1199.51
#Mann= 3 , 0 , 0
     9.8      .1       0  278.43    .045       0  297.95      .1       0
Bank Sta=278.43,297.95
XS Rating Curve= 0 ,0
Exp/Cntr=0.3,0.1

Type RM Length L Ch R = 1 ,3531.3  ,77.9,79.7,81.5
XS GIS Cut Line= 4
     1698834.173      206027.641     1698634.284       206101.99
     1698535.558      206200.716     1698408.799      206444.484
#Sta/Elev= 30
     9.7 1196.74    19.4 1189.82    29.1 1187.17    38.8 1182.83    58.2 1171.19
    77.6 1159.37    87.2 1149.87    96.9 1144.66   145.4 1122.19   155.1 1117.21
   164.8 1110.05   233.2 1078.37   253.2 1067.69   263.1  1063.9   283.1 1058.17
   293.1 1056.56   303.1 1057.81   332.9 1070.14   352.9 1080.34   362.7 1083.35
   372.5 1084.98   470.6 1123.57   480.5 1125.77   490.3 1129.49   500.1 1134.34
   539.3 1150.18   588.4 1172.56   598.2 1173.84     608 1177.84   627.6 1191.58
#Mann= 3 , 0 , 0
       0      .1       0   283.1    .045       0   303.1      .1       0
Bank Sta=283.1,303.1
XS Rating Curve= 0 ,0
Exp/Cntr=0.3,0.1

Type RM Length L Ch R = 1 ,3451.6  ,168.1,164.8,161.4
XS GIS Cut Line= 4
     1698798.827       205965.48     1698598.938      206034.954
     1698488.023      206131.242     1698324.699      206361.602
#Sta/Elev= 30
    10.1 1208.35    40.3 1190.17    50.4 1180.22    60.5 1173.38    90.7 1155.25
   120.9 1138.98   141.1 1123.66   191.5 1100.36   201.5 1094.85   211.6 1085.82
   250.8 1067.27   270.4 1060.13  296.02 1053.57   299.7 1052.42   309.5 1052.11
  315.31 1053.76   329.1 1056.74   338.9    1060   388.8 1081.19     419 1098.25
   439.2 1107.73   449.3 1111.48   459.3 1113.18   509.8 1133.67     540 1151.18
   560.2 1160.51   580.4 1166.78   620.7 1185.42   630.8 1191.66   640.9 1200.52
#Mann= 3 , 0 , 0
    10.1      .1       0  296.02    .045       0  315.31      .1       0
Bank Sta=296.02,315.31
XS Rating Curve= 0 ,0
Exp/Cntr=0.3,0.1

Type RM Length L Ch R = 1 ,3286.8  ,191.4,181.4,171.3
XS GIS Cut Line= 4
     1698587.968      205721.712     1698452.677      205932.571
     1698380.765      206014.234     1698251.569      206295.785
#Sta/Elev= 30
      10 1174.84      20 1168.46    30.1    1161    80.2 1129.45    90.2 1122.49
   110.2 1114.96   140.3 1091.72   150.3 1085.42   170.4 1075.75   190.4 1068.39
   200.4 1065.63   220.5 1063.68   250.5 1059.42   299.9  1050.2   309.9 1048.95
   319.9 1049.31   329.7 1053.02   349.4 1059.04   369.3 1067.82   399.3  1082.8
   439.3 1099.53   449.3 1102.82   459.3 1105.08   519.2 1137.35   539.2 1150.23
   549.2 1155.28   559.2 1156.68   609.2 1182.34   659.1 1210.69   669.1 1214.19
#Mann= 3 , 0 , 0
       0      .1       0   299.9    .045       0   319.9      .1       0
Bank Sta=299.9,319.9
XS Rating Curve= 0 ,0
Exp/Cntr=0.3,0.1

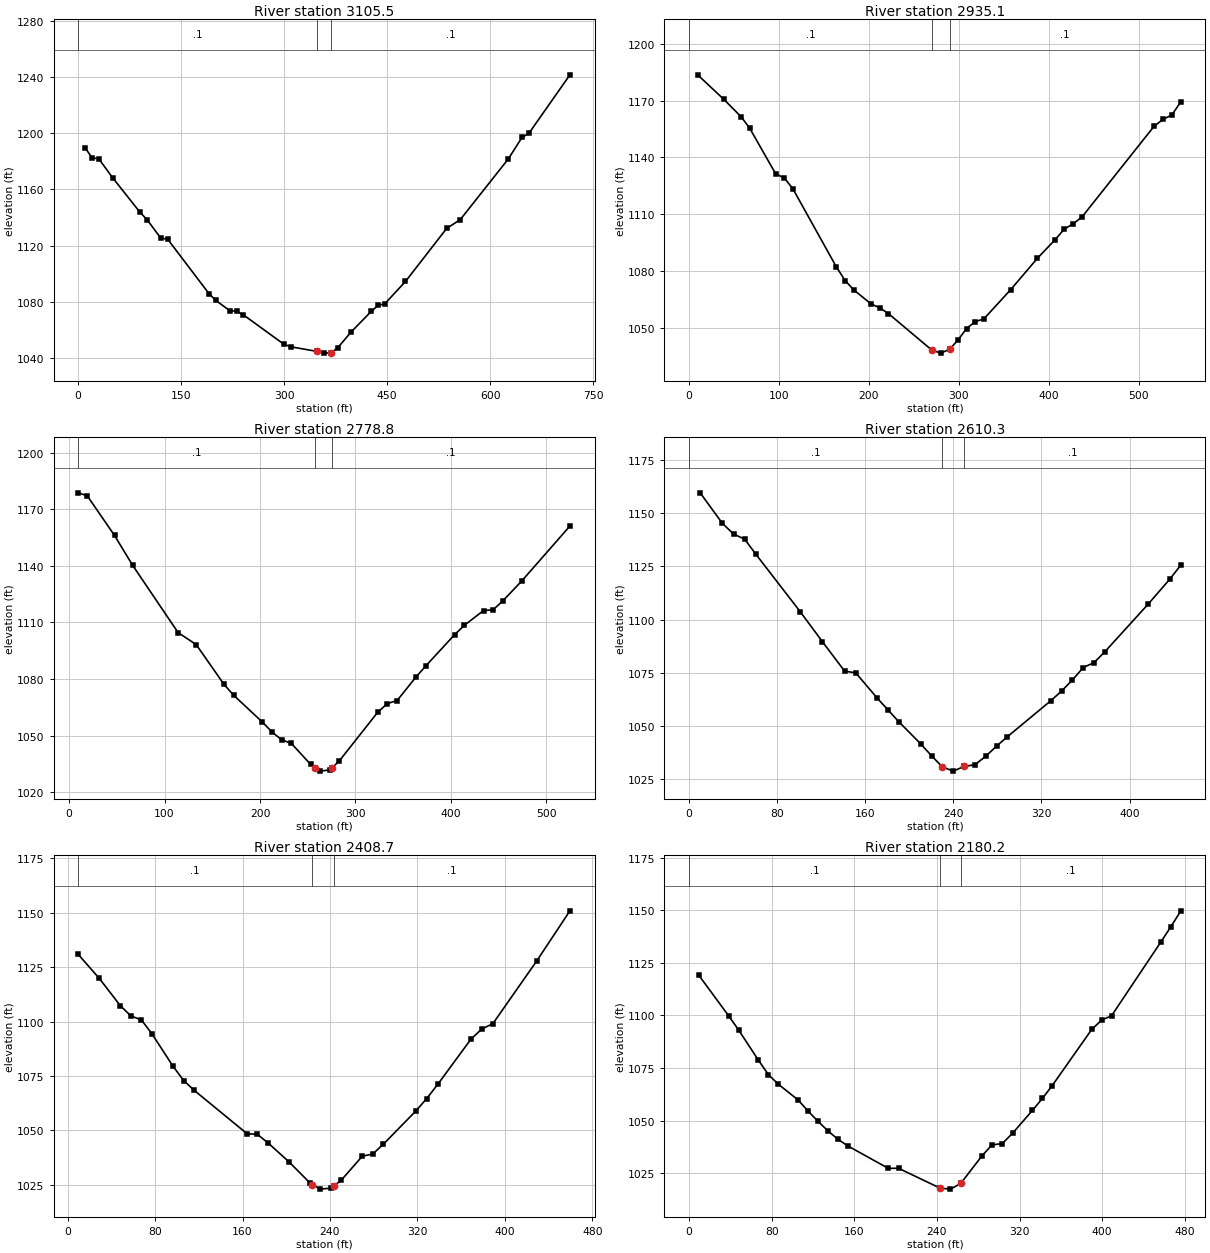
Type RM Length L Ch R = 1 ,3105.5  ,168.3,170.4,172.5
XS GIS Cut Line= 4
     1698261.319      205548.637      1698282.04      205798.499
     1698225.973       205965.48     1698136.998      206240.938
#Sta/Elev= 30
      10 1189.81    20.1 1182.52    30.1 1181.75    50.1 1168.39    90.3 1143.56
   100.3  1138.5   120.3 1125.31   130.4 1124.52   190.5  1085.8   200.6 1080.87
   220.6 1073.71   230.7 1073.19   240.7 1070.63   299.6 1049.74   309.4 1047.93
   348.4 1044.57   358.4 1043.38   368.4 1043.65   377.9 1047.07   397.5 1058.39
   426.9 1073.08   436.8 1077.31   446.8 1078.59   476.8 1094.42   536.7 1132.16
   556.6 1138.47   626.5 1181.64   646.5 1196.99   656.4 1199.79   716.3 1241.57
#Mann= 3 , 0 , 0
       0      .1       0   348.4    .045       0   368.4      .1       0
Bank Sta=348.4,368.4
XS Rating Curve= 0 ,0
Exp/Cntr=0.3,0.1

Type RM Length L Ch R = 1 ,2935.1  ,155.4,156.3,157.2
XS GIS Cut Line= 4
     1698182.095      205564.482     1698128.466      205749.746
     1698071.181      205882.599     1697991.956      206076.394
#Sta/Elev= 30
     9.6 1183.56    38.6 1170.67    57.9 1161.48    67.5  1155.4    96.4 1131.34
   106.1 1129.21   115.7 1123.32   163.9 1082.28   173.6 1075.11   183.2  1070.2
   202.5  1062.8   212.2 1060.74   221.8  1057.7   269.7 1038.61   279.7 1036.89
   289.7 1038.85     299 1043.77   308.6 1049.83   318.3 1053.48   327.9 1054.95
   357.5 1070.24   387.4 1086.87   407.3 1096.76   417.3 1102.28   427.3 1105.06
   437.2 1108.77     517 1156.35     527 1160.08   536.9 1162.39   546.9 1169.36
#Mann= 3 , 0 , 0
       0      .1       0   269.7    .045       0   289.7      .1       0
Bank Sta=269.7,289.7
XS Rating Curve= 0 ,0
Exp/Cntr=0.3,0.1

Type RM Length L Ch R = 1 ,2778.8  ,169.8,168.5,167.2
XS GIS Cut Line= 4
     1698055.336      205541.324     1697993.175      205680.272
     1697911.513      205853.347     1697878.604      206031.297
#Sta/Elev= 30
     9.5 1178.82      19 1177.28    47.6 1156.21    66.6 1140.34   114.2 1104.65
   133.2 1098.25   162.3 1077.14   172.4 1071.38   202.6 1057.08   212.7 1051.82
   222.7 1047.75   232.8 1045.84   252.9 1034.75  257.76 1032.96     263 1031.11
   273.1 1031.73  275.03 1032.61   283.2 1036.64   323.4 1062.43   333.5 1066.99
   343.6 1068.59   363.7 1081.27   373.8 1087.04   403.9 1103.58     414 1108.48
   434.1 1116.34   444.1 1116.74   454.2  1121.4   474.3 1132.12   524.6 1161.21
#Mann= 3 , 0 , 0
     9.5      .1       0  257.76    .045       0  275.03      .1       0
Bank Sta=257.76,275.03
XS Rating Curve= 0 ,0
Exp/Cntr=0.3,0.1

Type RM Length L Ch R = 1 ,2610.3  ,203.7,201.6,199.5
XS GIS Cut Line= 4
      1697861.54      205491.352     1697822.538      205637.613
     1697766.471      205774.122     1697723.812      205915.508
#Sta/Elev= 30
    10.1 1159.68    30.3 1145.29    40.4 1140.29    50.5 1137.86    60.5 1130.89
   100.9 1103.75   121.1 1089.59   141.3  1075.7   151.4 1074.89     171 1062.95
   180.9 1057.29   190.7 1051.77   210.4 1041.44   220.2 1035.84   229.9 1030.66
   239.9 1028.61   249.9 1030.84   259.6 1031.61   269.4 1035.59   279.3 1040.43
   289.1 1044.81   328.5 1061.76   338.3  1066.3   348.2 1071.58     358 1077.39
   367.9 1079.76   377.7 1084.88   417.1 1107.35   436.8 1119.16   446.6 1125.66
#Mann= 3 , 0 , 0
       0      .1       0   229.9    .045       0   249.9      .1       0
Bank Sta=229.9,249.9
XS Rating Curve= 0 ,0
Exp/Cntr=0.3,0.1

Type RM Length L Ch R = 1 ,2408.7  ,237.9,228.5,219.2
XS GIS Cut Line= 4
     1697675.058      205456.006     1697614.116      205608.361
     1697573.895      205736.338     1697533.673       205892.35
#Sta/Elev= 30
     9.7 1130.86      29 1119.83    48.3 1107.27    57.9 1102.58    67.6 1100.71
    77.2 1094.34    96.5 1079.44   106.2 1072.89   115.8 1068.41   164.1  1048.5
   173.7 1048.15   183.3 1044.27   202.4 1035.62   221.6  1025.9  223.83 1025.11
   231.2 1023.03   240.7 1023.49  243.48 1024.44   250.3 1027.12   269.5 1038.14
   279.1 1039.17   288.7 1043.61   318.4 1058.86   328.4 1064.61   338.5 1071.12
   368.7 1091.77   378.8 1096.59   388.9 1098.99   429.1 1127.86   459.4 1150.83
#Mann= 3 , 0 , 0
     9.7      .1       0  223.83    .045       0  243.48      .1       0
Bank Sta=223.83,243.48
XS Rating Curve= 0 ,0
Exp/Cntr=0.3,0.1

Type RM Length L Ch R = 1 ,2180.2  ,245.8,243.8,241.7
XS GIS Cut Line= 4
     1697331.346       205398.72     1697365.473      205568.139
     1697375.224      205708.305     1697391.069      205870.411
#Sta/Elev= 30
     9.6 1119.05    38.4 1099.81      48 1093.11    67.2 1078.71    76.8  1071.9
    86.4 1067.33   105.6 1059.81   115.2 1054.54   124.8 1049.67   134.4 1045.15
     144 1041.16   153.6 1037.99   192.9 1027.27   202.9  1027.3   243.1 1017.85
   253.1 1017.38   263.1 1020.07   283.2 1032.94   293.3 1038.43   303.3 1039.05
   313.3 1043.97   332.5 1054.83   342.1  1060.5   351.7 1066.65     390 1093.41
   399.6 1097.83   409.1 1099.84     457 1135.06   466.6 1142.26   476.2 1149.79
#Mann= 3 , 0 , 0
       0      .1       0   243.1    .045       0   263.1      .1       0
Bank Sta=243.1,263.1
XS Rating Curve= 0 ,0
Exp/Cntr=0.3,0.1

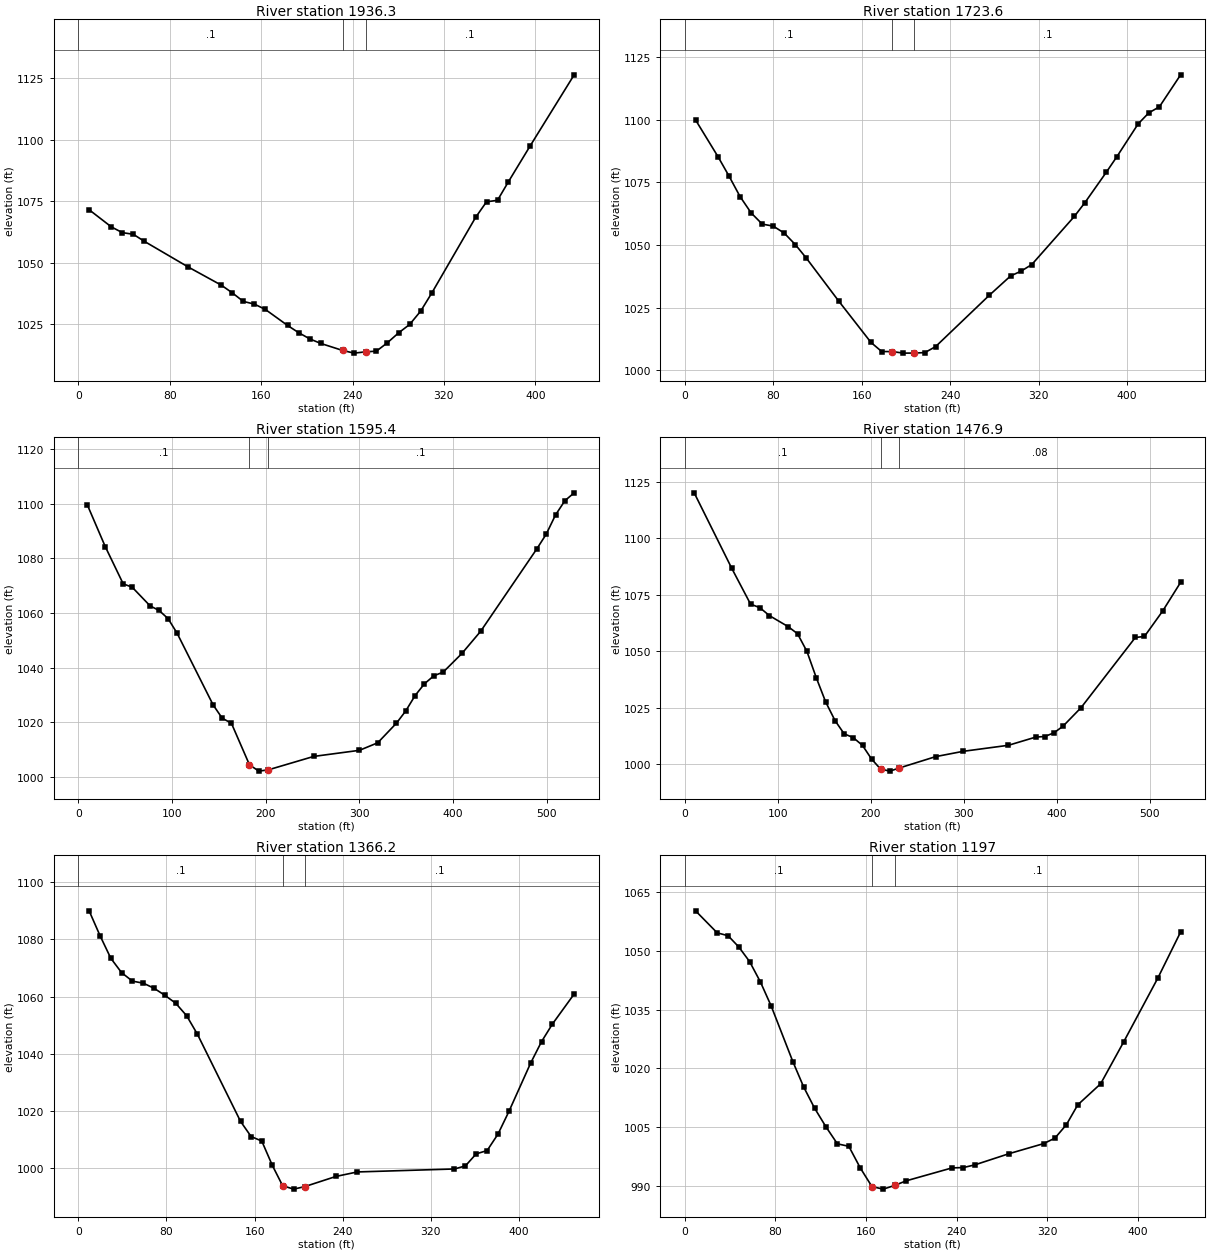
Type RM Length L Ch R = 1 ,1936.3  ,216.9,212.8,208.7
XS GIS Cut Line= 4
     1697110.736      205420.659     1697121.706      205583.984
     1697144.864      205718.056     1697192.398      205843.596
#Sta/Elev= 30
     9.6 1071.54    28.9 1064.63    38.5  1062.3    48.1 1061.63    57.8 1058.76
    96.3 1048.31   125.2 1040.95   134.8 1037.83   144.4 1034.36   154.1 1033.27
   163.7  1031.1   183.1 1024.62   192.8 1021.68   202.6 1019.14   212.3 1017.28
   231.4 1014.44   241.4 1013.36   251.4 1013.88   260.9 1014.16   270.6  1017.6
   280.3 1021.58     290    1025   299.7 1030.45   309.3 1037.71   347.7 1068.46
   357.3 1074.82   366.9 1075.43   376.5    1083   395.6 1097.61     434 1126.39
#Mann= 3 , 0 , 0
       0      .1       0   231.4    .045       0   251.4      .1       0
Bank Sta=231.4,251.4
XS Rating Curve= 0 ,0
Exp/Cntr=0.3,0.1

Type RM Length L Ch R = 1 ,1723.6  ,121.2,128.2,135.2
XS GIS Cut Line= 4
      1696886.47      205476.726     1696904.752      205585.203
     1696951.068      205733.901     1697046.138      205889.912
#Sta/Elev= 30
      10 1099.75      30  1085.3      40 1077.52      50 1069.32      60 1062.82
      70 1058.35      80 1057.54      90 1054.72     100 1050.14     110 1044.71
   139.2  1027.6   168.4 1011.07   178.1 1007.44   187.6 1007.44   197.6 1006.81
   207.6 1006.84   217.1 1007.02   226.8 1009.41   275.4 1029.93   294.6 1037.63
   304.2 1039.58   313.8 1042.19   352.3 1061.42   361.9 1066.96   381.1 1079.01
   390.8 1085.31     410 1098.39   419.6 1102.77   429.2  1105.2   448.4 1117.97
#Mann= 3 , 0 , 0
       0      .1       0   187.6    .045       0   207.6      .1       0
Bank Sta=187.6,207.6
XS Rating Curve= 0 ,0
Exp/Cntr=0.3,0.1

Type RM Length L Ch R = 1 ,1595.4  ,116.3,118.5,120.7
XS GIS Cut Line= 4
     1696796.276      205487.696     1696799.932      205621.768
     1696808.464      205807.031     1696940.099      205970.355
#Sta/Elev= 30
     9.6 1099.53    28.7 1084.29    47.9 1070.64    57.5 1069.41    76.6 1062.59
    86.2 1060.91    95.8 1057.92   105.4 1052.61   143.9 1026.36   153.6  1021.5
   163.4 1019.67   182.7 1004.45   192.7 1002.15   202.7 1002.61   251.3 1007.53
   300.1 1009.76   319.6 1012.51   339.6 1019.69   349.5 1024.16   359.5 1029.78
   369.5  1034.1   379.5 1037.02   389.5 1038.36   409.5 1045.19   429.5  1053.3
   489.4 1083.41   499.4 1088.77   509.4 1095.83   519.4 1101.05   529.3 1103.93
#Mann= 3 , 0 , 0
       0      .1       0   182.7    .045       0   202.7      .1       0
Bank Sta=182.7,202.7
XS Rating Curve= 0 ,0
Exp/Cntr=0.3,0.1

Type RM Length L Ch R = 1 ,1476.9  ,105.4,110.7,116
XS GIS Cut Line= 4
     1696701.206      205454.787      1696686.58      205615.673
     1696680.486      205763.153      1696624.42      205980.106
#Sta/Elev= 30
    10.1 1120.17    50.5 1086.75    70.7 1070.94    80.8 1069.32    90.9 1065.86
   111.1 1060.97   121.2 1057.84   131.3 1050.03   141.4 1038.35   151.5 1027.62
   161.6 1019.35   171.4 1013.52   181.2 1011.84   191.1 1008.39   200.9 1002.34
   210.6   997.9   220.6  997.02   230.6   998.4   269.8 1003.44   299.3 1005.78
   348.1 1008.46   377.4 1012.08   387.1 1012.34   396.8 1013.93   406.6 1016.85
   426.1 1025.09   484.5 1056.16   494.3 1056.62   513.8 1067.81   533.2 1080.56
#Mann= 3 , 0 , 0
       0      .1       0   210.6    .045       0   230.6     .08       0
Bank Sta=210.6,230.6
XS Rating Curve= 0 ,0
Exp/Cntr=0.3,0.1

Type RM Length L Ch R = 1 ,1366.2  ,170.4,169.3,168.1
XS GIS Cut Line= 4
     1696604.918      205465.756     1696587.855      205602.266
     1696552.508      205742.433     1696513.505      205905.757
#Sta/Elev= 30
     9.8    1090    19.7  1081.3    29.5 1073.39    39.3 1068.36    49.1 1065.41
      59 1064.69    68.8  1062.9    78.6 1060.43    88.4 1057.67    98.3  1053.3
   108.1 1046.82   147.2 1016.36   156.8 1011.05   166.5 1009.46   176.1 1000.93
   185.4  993.85   195.4  992.65   205.4  993.52   233.9   997.1   253.2  998.66
   341.4   999.7   351.3 1000.78   361.1 1004.99     371 1006.14   380.9 1011.92
   390.8 1019.83   410.5 1036.74   420.4 1044.25   430.3 1050.42     450  1060.9
#Mann= 3 , 0 , 0
       0      .1       0   185.4    .045       0   205.4      .1       0
Bank Sta=185.4,205.4
XS Rating Curve= 0 ,0
Exp/Cntr=0.3,0.1

Type RM Length L Ch R = 1 ,1197    ,294.7,300.3,305.9
XS GIS Cut Line= 4
     1696455.001      205470.632     1696418.436      205579.108
     1696385.527      205737.557     1696422.093      205894.788
#Sta/Elev= 30
     9.5 1060.31    28.6 1054.68    38.2 1053.95    47.7 1051.06    57.2 1047.34
    66.8  1042.1    76.3 1035.95    95.4 1021.75   104.9  1015.3   114.5 1009.89
   124.6 1005.09   134.7 1000.74   144.8 1000.11   154.9  994.58   165.2  989.81
   175.2  989.16   185.2   990.1   195.4  991.28   235.8  994.58     246  994.68
   256.1  995.37   286.4  998.24   316.7 1000.79   326.7 1002.19   336.8 1005.61
   346.9 1010.71   367.1 1016.09   387.3 1026.73   417.6 1043.13   437.7 1054.91
#Mann= 3 , 0 , 0
       0      .1       0   165.2    .045       0   185.2      .1       0
Bank Sta=165.2,185.2
XS Rating Curve= 0 ,0
Exp/Cntr=0.3,0.1

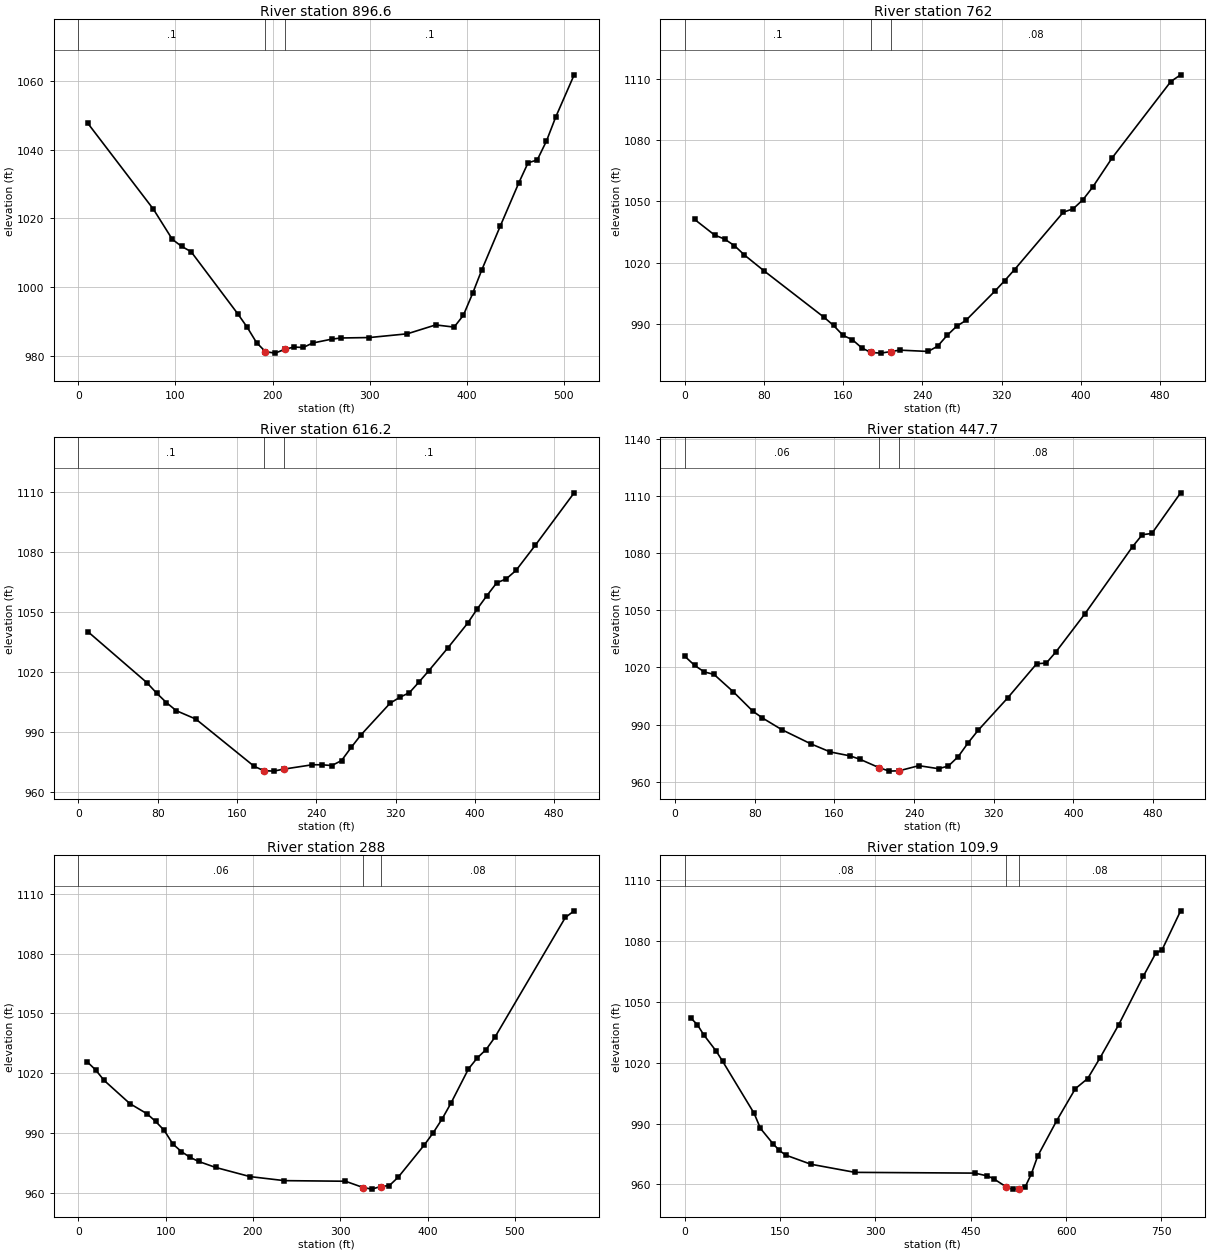
Type RM Length L Ch R = 1 ,896.6   ,129.5,134.6,139.7
XS GIS Cut Line= 5
     1696247.799       205398.72     1696161.534      205503.222
     1696122.646      205591.056     1696203.775      205700.764
     1696126.222      205820.399
#Sta/Elev= 30
     9.7  1047.7    77.4 1022.61    96.8 1013.86   106.5 1011.79   116.1 1010.28
   164.3  992.13   173.9  988.25   183.5  983.79   192.7  981.14   202.7  980.72
   212.7  981.84     222  982.49   231.6  982.37   241.3  983.66   260.8  984.79
   270.5  985.13   299.8  985.26   338.8  986.35     368  988.94     387   988.3
   396.5  991.74     406  998.09   415.5 1004.98   434.5 1017.72   453.6 1030.32
   463.1 1036.15   472.6    1037   482.1 1042.52   491.6 1049.48   510.6 1061.79
#Mann= 3 , 0 , 0
       0      .1       0   192.7    .045       0   212.7      .1       0
Bank Sta=192.7,212.7
XS Rating Curve= 0 ,0
Exp/Cntr=0.3,0.1

Type RM Length L Ch R = 1 ,762     ,152.7,145.8,138.9
XS GIS Cut Line= 4
      1696130.79      205337.778     1696049.128      205452.349
     1695960.153      205576.671     1695874.834       205765.59
#Sta/Elev= 30
      10 1041.17    30.1 1033.55    40.2 1031.58    50.2 1028.34    60.3 1023.74
    80.4 1015.87   140.7  993.25   150.3  989.24   159.8  984.43   169.4  982.24
   178.9  978.21     188  976.03     198   975.7     208  976.45   217.1  977.17
   245.8  976.52   255.4  979.09   264.9  984.35   274.5   988.8     284  991.75
   313.3 1006.09   323.2 1011.23   333.1 1016.61   382.4 1044.74   392.3  1046.4
   402.2 1050.84     412 1056.99   431.8 1071.41     491 1108.77   500.9 1112.05
#Mann= 3 , 0 , 0
       0      .1       0     188    .045       0     208     .08       0
Bank Sta=188,208
XS Rating Curve= 0 ,0
Exp/Cntr=0.3,0.1

Type RM Length L Ch R = 1 ,616.2   ,178,168.5,159
XS GIS Cut Line= 4
     1695999.156      205271.961     1695908.962      205376.781
     1695849.239      205542.543     1695800.485      205721.712
#Sta/Elev= 30
     9.9 1040.27    69.1 1014.92      79 1009.66    88.9 1004.91    98.8 1000.89
   118.5   996.7   177.4  973.07     187  970.92     197  970.67     207  971.65
   236.2  973.86     246  973.83   255.7  973.46   265.5  975.94   275.3  982.54
   285.1  988.77   314.5 1004.61   324.2 1007.54     334 1009.88   343.8 1015.28
   353.6 1020.88   373.1 1032.46   392.7 1044.58   402.4 1051.74   412.2 1058.41
     422 1064.74   431.7 1066.79   441.5 1070.97   461.1 1083.64   500.2 1109.78
#Mann= 3 , 0 , 0
       0      .1       0     187    .045       0     207      .1       0
Bank Sta=187,207
XS Rating Curve= 0 ,0
Exp/Cntr=0.3,0.1

Type RM Length L Ch R = 1 ,447.7   ,155.9,159.7,163.5
XS GIS Cut Line= 4
     1695832.175      205213.457      1695726.91      205341.226
     1695733.449      205519.385     1695687.133      205676.615
#Sta/Elev= 30
     9.7 1025.85    19.5 1021.11    29.2 1017.64      39 1016.36    58.4 1007.23
    77.9  997.11    87.6  993.51   107.1  987.36   136.3  979.91   155.8  975.66
   175.5  973.62   185.4  971.87   205.1  967.36   215.1   965.6   225.1   965.8
   244.8  968.46   264.6  966.87   274.5   968.3   284.4  973.26   294.3  980.48
   304.2  986.94   333.9 1003.95   363.1 1021.94   372.8  1022.3   382.4 1028.11
   411.3 1047.94   459.5 1083.42   469.2 1089.63   478.8 1090.28   507.7  1111.6
#Mann= 3 , 0 , 0
     9.7     .06       0   205.1    .045       0   225.1     .08       0
#XS Ineff= 2 , 0
       0                     244       0
Permanent Ineff=
       F       F
Bank Sta=205.1,225.1
XS Rating Curve= 0 ,0
Exp/Cntr=0.3,0.1

Type RM Length L Ch R = 1 ,288     ,177.8,178.1,178.3
XS GIS Cut Line= 4
     1695807.798      205204.925     1695581.094      205323.152
     1695561.593       205482.82     1695567.687      205633.956
#Sta/Elev= 30
     9.8 1025.86    19.7 1021.72    29.5 1016.41      59 1004.75    78.7  999.62
    88.5   995.8    98.3  991.34   108.2  984.49     118  980.66   127.8  977.81
   137.7  975.72   157.3  972.69   196.7  968.09     236  966.07   305.9  965.77
   326.1  962.62   336.1  961.81   346.1   963.1   356.2  963.61   366.3  967.79
   396.4   984.1   406.5  990.17   416.5  996.98   426.6 1004.88   446.8 1022.19
   456.9 1027.71     467  1031.9     477 1038.04   557.7 1098.18   567.8 1101.53
#Mann= 3 , 0 , 0
       0     .06       0   326.1    .045       0   346.1     .08       0
Bank Sta=326.1,346.1
XS Rating Curve= 0 ,0
Exp/Cntr=0.3,0.1

Type RM Length L Ch R = 1 ,109.9   ,113.1,109.9,106.8
XS GIS Cut Line= 4
     1695810.236      205170.797     1695403.144      205328.028
     1695382.424      205485.258     1695454.335      205655.895
#Sta/Elev= 30
     9.9 1041.79    19.8 1038.63    29.8 1033.66    49.6 1025.55    59.5 1020.64
   109.1     995     119  987.62   138.9  980.01   148.8  976.76   158.7  974.48
   198.4  969.97   267.8  965.97   456.2   965.6     476  964.23     486  962.83
   505.7  958.84   515.7  957.72   525.7  957.75   535.5  958.72   545.4  965.28
   555.3  973.99   585.1  991.35   614.5 1007.13     634 1012.15   653.5 1022.36
   682.7 1038.58   721.7  1062.6   741.2 1073.89   750.9 1075.41   780.2 1094.67
#Mann= 3 , 0 , 0
       0     .08       0   505.7    .045       0   525.7     .08       0
Bank Sta=505.7,525.7
XS Rating Curve= 0 ,0
Exp/Cntr=0.3,0.1

Chan Stop Cuts=-1
Use User Specified Reach Order=0